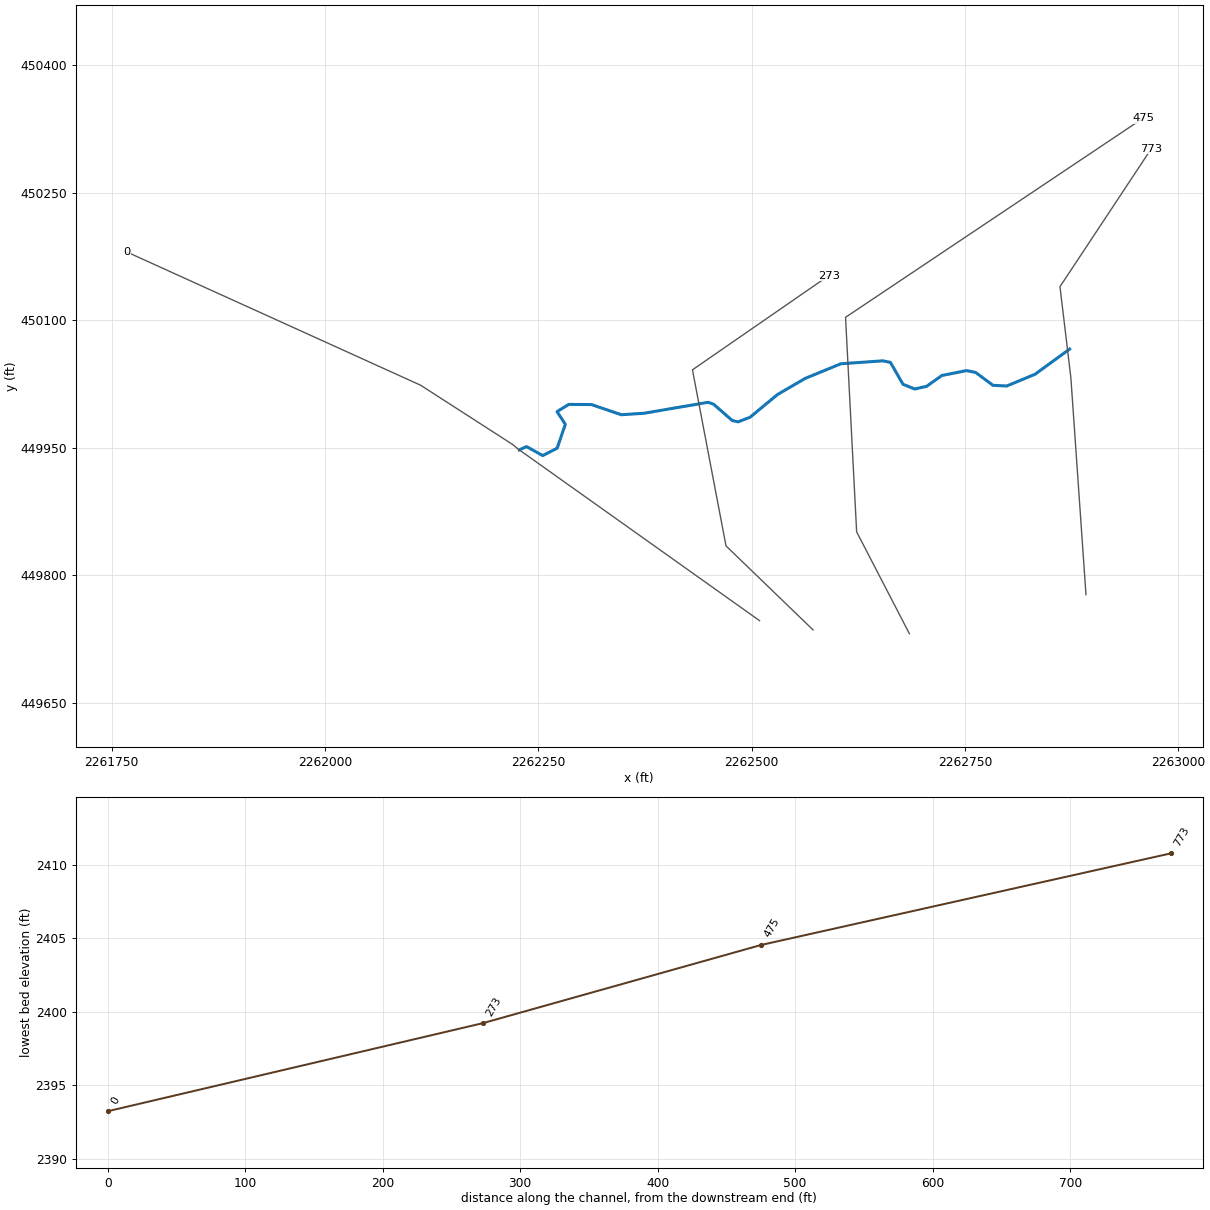
--- BRWNSCKT1.prj (project) ---

Proj Title=BRWNSCKT1
Current Plan=p01
Default Exp/Contr=0.3,0.1
English Units
Geom File=g01
Flow File=f01
Plan File=p01
Y Axis Title=Elevation
X Axis Title(PF)=Main Channel Distance
X Axis Title(XS)=Station
BEGIN DESCRIPTION:
----------MODEL BY WOOD PLC 2021----------
Stream Name: Browns Creek Tributary 1
Flood Zone: Enhanced Approximate
Pocahontas County, WV
HEC-RAS Version: RAS 6.1
Vertical Datum: NAVD88
Projection: NAD 1983 StatePlane West Virginia S FIPS 4702 (US Feet)
Terrain: 1-meter LIDAR (FEMA Region III 3DEP collected 2016-2018)
Land Use: 2019 NLCD
Hydrologic Method:
WV SIR2010-5033 regression equations
Model Notes:
KWSELtie in with BROWNSCK at XS 24636
END DESCRIPTION:
DSS Export Rating Curves= 0
DSS Export Rating Curve Sorted= 0
DSS Export Volume Flow Curves= 0
DXF OffsetX= 0
DXF OffsetY= 0
DXF ScaleX= 1
DXF ScaleY= 10

--- BRWNSCKT1.p01 (plan) ---

Plan Title=Floodplain
Program Version=6.10
Short Identifier=Floodplain
Geom File=g01
Flow File=f01
Subcritical Flow
K Sum by GR= 0
Std Step Tol= 0.01
Critical Tol= 0.01
Num of Std Step Trials= 20
Max Error Tol= 0.3
Flow Tol Ratio= 0.001
Split Flow NTrial= 30
Split Flow Tol= 0.02
Split Flow Ratio= 0.02
Log Output Level= 0
Friction Slope Method= 1
Unsteady Friction Slope Method= 2
Unsteady Bridges Friction Slope Method= 1
Parabolic Critical Depth
Global Vel Dist= 0 , 0 , 0
Global Log Level= 0
CheckData=True
Encroach Param=-1 ,0,0, 0
Computation Interval=1MIN
Output Interval=1HOUR
Instantaneous Interval=1HOUR
Mapping Interval=1HOUR
Computation Time Step Use Courant=        0
Computation Time Step Use Time Series=    0
Computation Time Step Count To Double=0
Computation Time Step Max Doubling=0
Computation Time Step Max Halving=0
Computation Time Step Residence Courant=0
Run HTab= 0
Run UNet= 0
Run Sediment= 0
Run PostProcess= 0
Run WQNet= 0
Run RASMapper=-1
UNET Theta= 1
UNET Theta Warmup= 1
UNET ZTol= 0.02
UNET ZSATol= 0.02
UNET MxIter= 20
UNET Max Iter WO Improvement= 0
UNET MaxInSteps= 0
UNET DtIC= 0
UNET DtMin= 0
UNET MaxCRTS= 20
UNET WFStab= 2
UNET SFStab= 1
UNET WFX= 1
UNET SFX= 1
UNET Gravity=32.174
UNET 1D Methodology=Finite Difference
UNET DSS MLevel= 4
UNET Pardiso=0
UNET DZMax Abort= 100
UNET Use Existing IB Tables=-1
UNET Froude Reduction=False
UNET Froude Limit= 0.8
UNET Froude Power= 4
UNET D1 Cores= 0
UNET WindReference=Eulerian
UNET WindDragFormulation=Hsu (1988)
UNET D2 Coriolis=0
UNET D2 Cores= 0
UNET D2 Theta= 1
UNET D2 Theta Warmup= 1
UNET D2 Z Tol= 0.01
UNET D2 Volume Tol= 0.01
UNET D2 Max Iterations= 20
UNET D2 Equation= 0
UNET D2 RampUpFraction=0.1
UNET D2 TimeSlices= 1
UNET D2 Turbulence Formulation=None
UNET D2 Eddy Viscosity=0.3
UNET D2 Transverse Eddy Viscosity=0.1
UNET D2 Smagorinsky Mixing=0.05
UNET D2 BCVolumeCheck=0
UNET D2 Cores=0
UNET D2 SolverType=PARDISO (Direct)
UNET D2 Minimum Iterations= 2147483647
UNET D2 Maximum Iterations= 2147483647
UNET D2 Restart Number= 10
UNET D2 Relaxation Coeff=1.3
UNET D2 SOR Precondition Iterations= 10
UNET D2 ILUT Maximum Fill= 8
UNET D2 ILUT Tolerance=1E-08
UNET D1D2 MaxIter= 0
UNET D1D2 ZTol=0.01
UNET D1D2 QTol=0.1
UNET D1D2 MinQTol=1
Write IC File= 0
Write IC File at Fixed DateTime=0
Write IC File at Sim End=0
Echo Input=False
Echo Parameters=False
Echo Output=False
Write Detailed= 0
HDF Write Warmup=0
HDF Write Time Slices=0
HDF Flush=0
HDF Compression= 1
HDF Chunk Size= 1
HDF Spatial Parts= 1
HDF Use Max Rows=0
HDF Fixed Rows= 1
Calibration Method= 0
Calibration Iterations= 20
Calibration Max Change=0.05
Calibration Tolerance=0.2
Calibration Maximum=1.5
Calibration Minimum=0.5
Calibration Optimization Method= 1
WQ AD Non Conservative
WQ ULTIMATE=-1
WQ Max Comp Step=1HOUR
WQ Output Interval=15MIN
WQ Output Selected Increments= 0
WQ Output face flow=0
WQ Output face velocity=0
WQ Output face area=0
WQ Output face dispersion=0
WQ Output cell volume=0
WQ Output cell surface area=0
WQ Output cell continuity=0
WQ Output cumulative cell continuity=0
WQ Output face conc=0
WQ Output face dconc_dx=0
WQ Output face courant=0
WQ Output face peclet=0
WQ Output face adv mass=0
WQ Output face disp mass=0
WQ Output cell mass=0
WQ Output cell source sink temp=0
WQ Output nsm pathways=0
WQ Output nsm derived pathways=0
WQ Create Restart=0
WQ Fixed Restart=0
WQ System Summary=0
WQ Write To DSS=0
Sorting and Armoring Iterations= 10
XS Update Threshold= 0.02
Bed Roughness Predictor= 0
Hydraulics Update Threshold= 0.02
Energy Slope Method= 1
Volume Change Method= 1
Sediment Retention Method= 0
Sediment TS Multiplier= 1
Warm Up Method= 0
XS Weighting Method= 0
Number of US Weighted Cross Sections= 1
Number of DS Weighted Cross Sections= 1
Upstream XS Weight=0
Main XS Weight=1
Downstream XS Weight=0
Number of DS XS's Weighted with US Boundary= 1
Upstream Boundary Weight= 1
Weight of XSs Associated with US Boundary= 0
Number of US XS's Weighted with DS Boundary= 1
Downstream Boundary Weight= 0.5
Weight of XSs Associated with DS Boundary= 0.5
Percentile Method= 0
Sediment Output Level= 3
Mass or Volume Output= 0
Output Increment Type= 1
Profile and TS Output Increment= 1
Transport Output Increment 1
XS Output Flag= 0
XS Output Increment= 10
Read HDF5 Sediment Hotstart= 0
Sediment Hotstart Type= 0
Write Gradation File= 0
Read Gradation Hotstart= 0
Write HDF5 File= 1
Write Binary Output= 1
Write DSS Sediment File= 0
DSS Sediment Output Type= 1
SV Curve= 0
Specific Gage Flag= 0
Subcell Erosion Methods= 0
Subcell Deposition Methods= 0
Advection Scheme= 1
Matrix Solver= 0
Implicit Weighting Factor= 1
Maximum Outer Loop Convergence Iterations= 5
Convergence Maximum Absolute= 0.001
Convergence RMSE= 0.0001
Grain Fractions Max Abs Error= 0.001
Max Subgrid Regions= 1
Max Subgrid Length Scale= 3.402823E+38
Initial Layer Thickness= 3.402823E+38
Min Layer Thickness= 3.402823E+38
Max Layer Thickness= 3.402823E+38
Number of Layers= 5

--- BRWNSCKT1.f01 (steady flow) ---

Flow Title=Flow
Program Version=6.10
Number of Profiles= 6
Profile Names=01pct,10pct,04pct,02pct,0_2pct,01plus
River Rch & RM=BRWNSCKT1,Main            ,773
     718     383     507     609     998    1060
River Rch & RM=BRWNSCKT1,Main            ,0
     801     429     567     680    1110    1180
Boundary for River Rch & Prof#=BRWNSCKT1,Main            , 1
Up Type= 0
Dn Type= 1
Dn Known WS=2397.4
Boundary for River Rch & Prof#=BRWNSCKT1,Main            , 2
Up Type= 0
Dn Type= 1
Dn Known WS=2396.5
Boundary for River Rch & Prof#=BRWNSCKT1,Main            , 3
Up Type= 0
Dn Type= 1
Dn Known WS=2396.9
Boundary for River Rch & Prof#=BRWNSCKT1,Main            , 4
Up Type= 0
Dn Type= 1
Dn Known WS=2397.2
Boundary for River Rch & Prof#=BRWNSCKT1,Main            , 5
Up Type= 0
Dn Type= 1
Dn Known WS=2397.8
Boundary for River Rch & Prof#=BRWNSCKT1,Main            , 6
Up Type= 0
Dn Type= 1
Dn Known WS=2397.9
DSS Import GetInterval= 0
DSS Import GetPeak= 0
DSS Import FillOption= 0

--- BRWNSCKT1.g01 (geometry) ---

Geom Title=Geometry
Program Version=6.10

River Reach=BRWNSCKT1       ,Main
Reach XY= 30
2262872.70980376450066.1621735382262832.25433808450036.569749573
2262798.91603767450022.7100067042262782.82020408 450023.58257019
2262762.47020875450038.7122296432262751.89485672450040.852859813
2262723.05410468450035.1289474552262705.13769373450022.408295684
2262691.14913025450019.1587650192262677.38618082 450024.81140496
2262662.67579979450050.5370608672262653.89675843450052.328701961
2262604.63916245450048.8965664492262562.85878027450031.692879671
2262530.41754235450012.7688242162262498.20314733449986.037981467
  2262484.213355449980.5733532462262477.33188029449982.047954969
2262455.38892032450001.322853335 2262449.0475911450003.550887927
2262373.61822572449990.6497983582262347.32116164449988.929429681
2262312.21005149450000.8803033832262285.70878423450001.065488302
2262271.90258698449992.5913396422262281.61453263449977.642560544
2262271.99780213449949.5540902662262255.14471996449940.889511299
2262236.19690442449951.4583933362262227.68060336449947.578968625

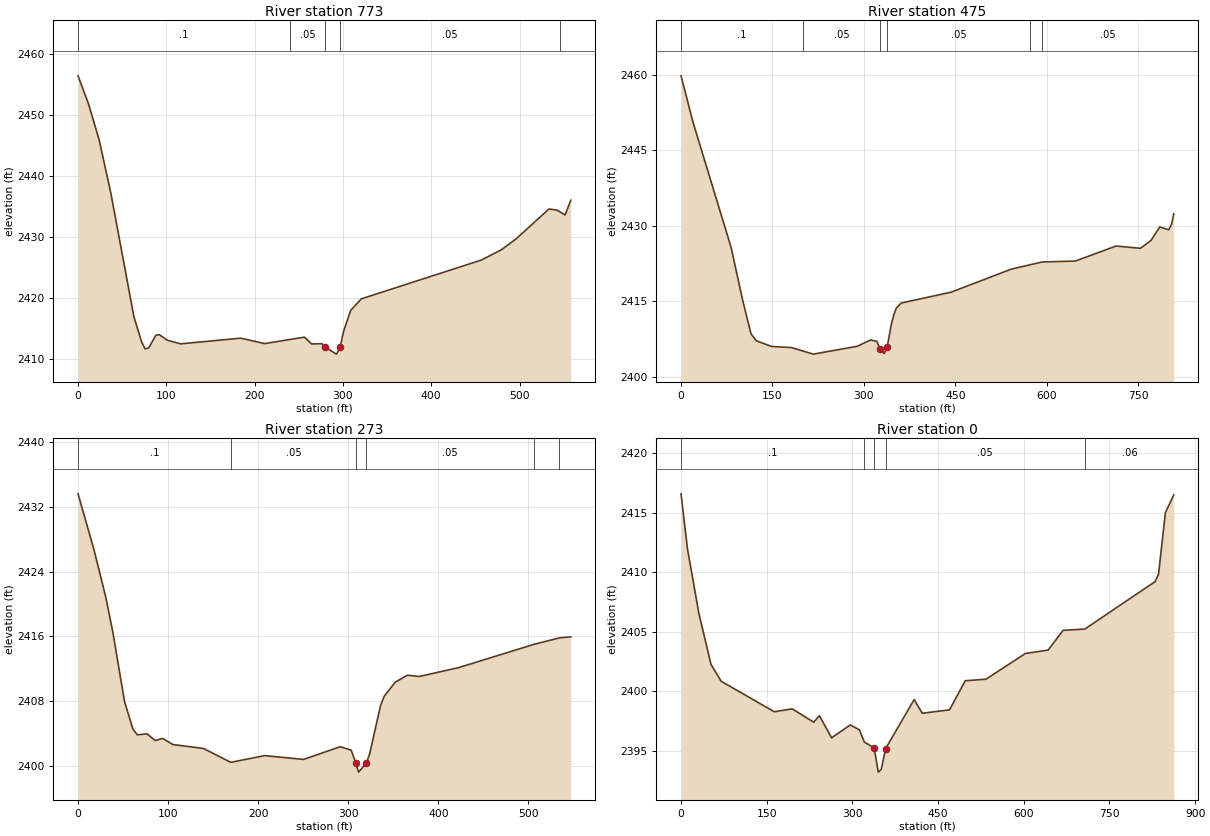
Type RM Length L Ch R = 1 ,773     ,297.9,297.9,297.9
XS GIS Cut Line= 4
2262891.89365404449777.3248519932262874.20959027450032.270104749
  2262861.418004450139.5533243192262968.52459707450301.952077318
#Sta/Elev= 30
       0 2456.47    11.9 2451.83    23.9 2445.96    37.1 2437.24    63.3 2416.89
      72 2412.77      76 2411.64      80 2411.78    88.1 2413.88    92.1 2413.96
   100.8 2413.07   116.1 2412.46   184.3 2413.39   211.3  2412.5   256.5 2413.56
   264.5 2412.44   276.2 2412.48   279.8 2411.93   292.7 2410.77   296.8  2411.9
   300.8 2414.55   308.8 2417.96   320.9 2419.85   456.6 2426.21   479.4  2427.9
   496.7 2429.77   533.3  2434.6   542.6 2434.42   551.6 2433.62   558.1 2436.04
#Mann= 5 ,-1,0
       0      .1       0     240     .05       0   279.8    .045       0
   296.8     .05       0  546.04     .06       0
Bank Sta=279.8,296.8
XS Rating Curve= 0 ,0
Exp/Cntr=0.3,0.1

Type RM Length L Ch R = 1 ,475     ,172.1,202.4,184.2
XS GIS Cut Line= 4
2262684.91507485449731.3613574962262623.08037273449851.129508875
2262610.06486105450103.5250172872262959.19312103 450337.96796084
#Sta/Elev= 30
       0 2459.82    19.7 2450.58    82.1 2425.75   101.1 2415.24   114.7 2408.57
   123.6 2407.19   148.9 2406.05   180.9 2405.85   216.9 2404.54     289  2406.1
   310.9 2407.36   321.1 2407.07   326.1 2405.65   333.1 2404.64  338.022405.914
     345 2410.51   349.1 2412.41   353.1 2413.69   361.1 2414.69   443.1 2416.85
   541.2 2421.41     592 2422.84   646.8 2423.03   713.4 2426.01   753.4 2425.56
   770.8 2427.14   785.1 2429.81   799.6 2429.24   804.4 2430.29   808.1 2432.41
#Mann= 6 ,-1,0
       0      .1       0   200.4     .05       0   326.1    .045       0
  338.02     .05       0   572.1     .06       0     592     .05       0
Bank Sta=326.1,338.02
XS Rating Curve= 0 ,0
Exp/Cntr=0.3,0.1

Type RM Length L Ch R = 1 ,273     ,184.4,272.8,251.1
XS GIS Cut Line= 4
2262571.91758816449735.8922236172262469.96664443449834.632114006
2262430.63124094450041.745054823 2262590.3811449450152.526395259
#Sta/Elev= 30
       0 2433.61    17.7  2426.7    30.6 2420.93    38.6 2416.54    51.6 2407.94
    60.9 2404.54    65.8 2403.83    76.6 2403.95    85.6 2403.13    94.1 2403.38
   105.3 2402.63   139.3 2402.14   169.6 2400.43   207.2 2401.26   250.4 2400.79
   291.1 2402.36   303.3 2401.93  308.45 2400.32   311.5 2399.22   320.1 2400.34
   323.7 2401.44   335.9 2407.46     340 2408.61   352.2 2410.33   365.8  2411.2
     379 2411.04   422.8 2412.14   506.2 2415.01   534.5 2415.81547.1462 2415.94
#Mann= 6 ,-1,0
       0      .1       0   169.6     .05       0  308.45    .045       0
   320.1     .05       0   506.2     .06       0   534.5     .05       0
Bank Sta=308.45,320.1
XS Rating Curve= 0 ,0
Exp/Cntr(USF)=0,0
Exp/Cntr=0.3,0.1

Type RM Length L Ch R = 1 ,0       ,,,
XS GIS Cut Line= 5
2262509.31809626449746.6696548482262225.80277472449948.918539073
2262219.94716614449953.8732847952262112.03275576450023.626354081
2261767.84138109 450180.28488674
#Sta/Elev= 30
       0 2416.59    11.2    2412    31.3 2406.54    52.5 2402.27    70.2 2400.86
   163.2  2398.3   194.8 2398.54   232.3 2397.42   242.2 2397.97   263.6 2396.11
   296.2 2397.19   312.3 2396.78   320.8 2395.76   338.1 2395.26   345.3 2393.23
   350.4 2393.46   358.2 2395.21   408.1 2399.32   422.3 2398.17     470 2398.46
   497.5  2400.9   533.8 2401.03   602.9 2403.19   642.5 2403.47   668.9 2405.13
   706.9 2405.24   829.8 2409.22   835.9 2409.85   847.9 2415.02   862.6  2416.5
#Mann= 5 ,-1,0
       0      .1       0   320.8     .05       0   338.1    .045       0
   358.2     .05       0   706.9     .06       0
Bank Sta=338.1,358.2
XS Rating Curve= 0 ,0
Exp/Cntr=0.3,0.1
LCMann Table=0

Chan Stop Cuts=-1
Use User Specified Reach Order=0
Composite Channel Slope=5